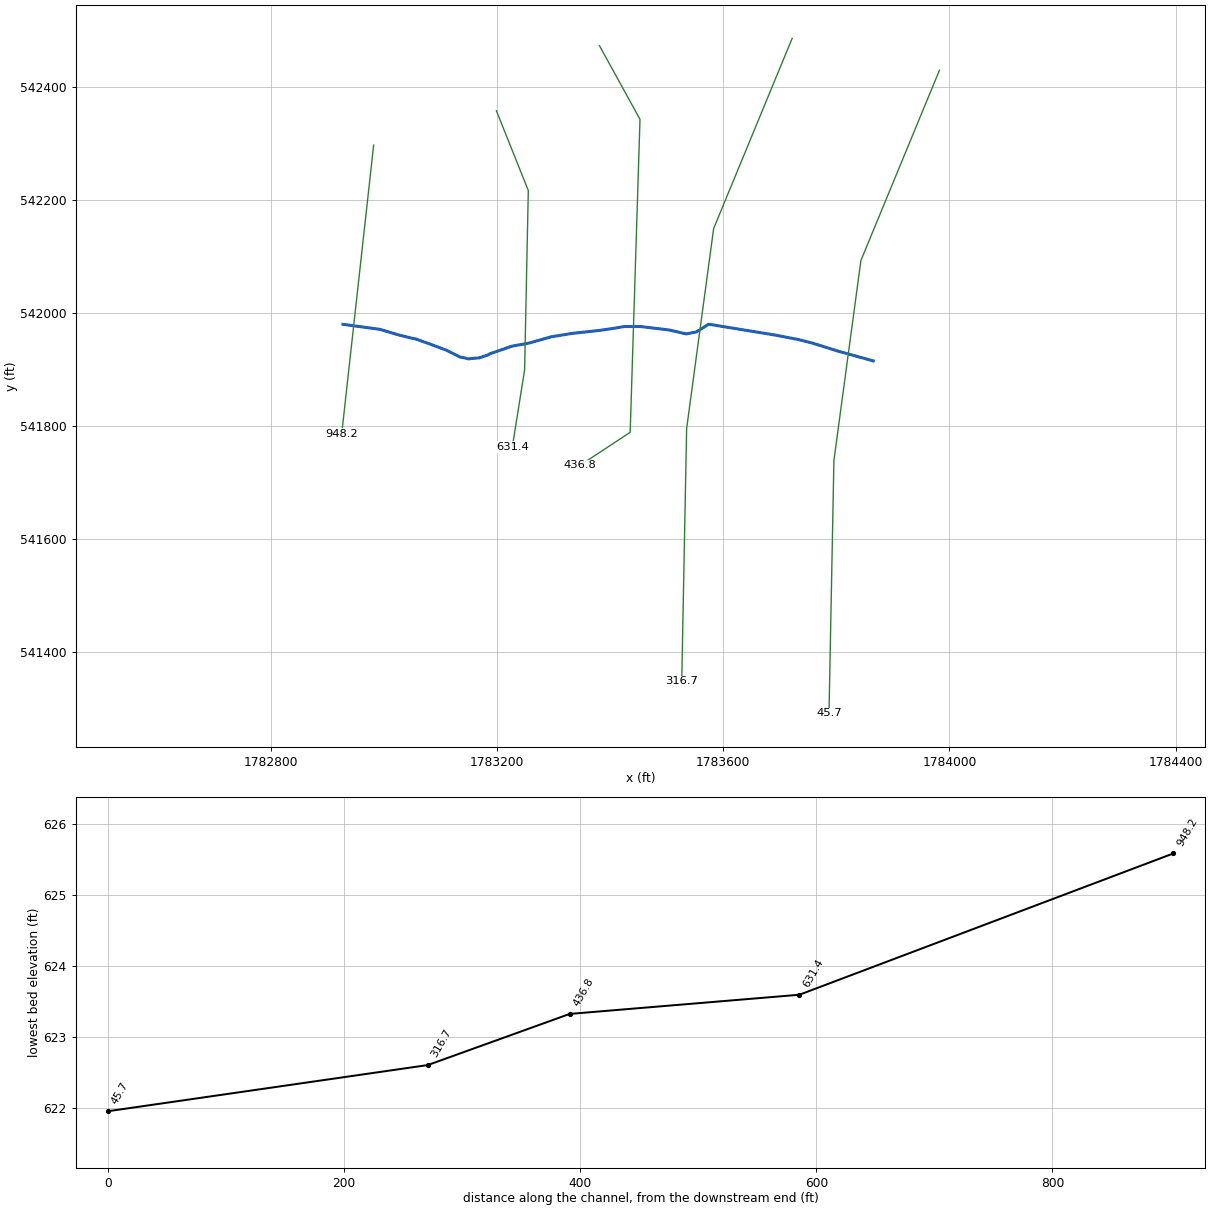
--- CLAYLICKBR.prj (project) ---

Proj Title=CLAYLICKBR
Current Plan=p01
Default Exp/Contr=0,0
English Units
Geom File=g01
Flow File=f01
Plan File=p01
BEGIN DESCRIPTION:
END DESCRIPTION:
DSS Export Rating Curves= 0
DSS Export Rating Curve Sorted= 0
DSS Export Volume Flow Curves= 0
DXF OffsetX= 0
DXF OffsetY= 0
DXF ScaleX= 0
DXF ScaleY= 0

--- CLAYLICKBR.p01 (plan) ---

Plan Title=Floodplain
Program Version=4.00
Geom File=g01
Flow File=f01
K Sum by GR=0
Std Step Tol=0.01
Critical Tol=0.01
Num of Std Step Trials=20
Max Error Tol=0.3
Flow Tol Ratio=0.001
Split Flow NTrial=30
Split Flow Tol=0.02
Split Flow Ratio=0.02
Log Output Level=0
Friction Slope Method=1
Unsteady Friction Slope Method=2
Unsteady Bridges Friction Slope Method=1
Global Log Level=0
CheckData=False
Run HTab=0
Run UNet=0
Run PostProcess=0
UNET Theta=0
UNET Theta Warmup=0
UNET ZTol=0
UNET ZSATol=0
UNET MxIter=0
UNET MaxInSteps=0
UNET DtIC=0
UNET DtMin=0
UNET MaxCRTS=0
UNET WFStab=0
UNET SFStab=0
UNET WFX=0
UNET SFX=0
UNET DSS MLevel=0
UNET DZMax Abort=0
UNET Convert EG Bridges=0
UNET Use Existing IB Tables=0
UNET Froude Limit=0
UNET Froude Power=0
Write IC File=0
Echo Input=False
Echo Output=False
Write Detailed=0

--- CLAYLICKBR.f01 (steady flow) ---

Flow Title=NFF Regression Equation
Program Version=4.10
Number of Profiles= 1
Profile Names=P100yr
River Rch & RM=CLAYLICKBR,Main            ,948.2
 887.798
Boundary for River Rch & Prof#=CLAYLICKBR,Main            , 1
Up Type= 0
Dn Type= 3
Dn Slope=0.003
DSS Import GetInterval= 0
DSS Import GetPeak= 0
DSS Import FillOption= 0

--- CLAYLICKBR.g01 (geometry) ---

Geom Title=USGS 10m DEM
Program Version=4.10

River Reach=CLAYLICKBR      ,Main
Reach XY= 29
      1782927.78      541979.994     1782993.382      541971.025
     1783028.104      541960.609     1783057.618      541953.664
     1783081.924      541944.983     1783109.701      541934.567
     1783134.007      541922.414     1783149.632      541918.942
     1783168.729      541920.678     1783184.354      541925.886
     1783187.203      541927.786      1783209.03      541935.289
     1783226.391      541941.365     1783255.905      541946.574
     1783295.836      541957.858     1783333.162      541963.935
     1783380.905      541969.143     1783405.211      541972.615
     1783425.176      541976.087     1783453.822      541976.087
     1783504.169      541970.011     1783534.551      541963.067
      1783552.78      541966.539     1783574.427      541980.168
     1783692.615       541960.85     1783734.411      541952.792
     1783758.509      541946.574      1783802.78      541932.685
      1783865.28      541915.324

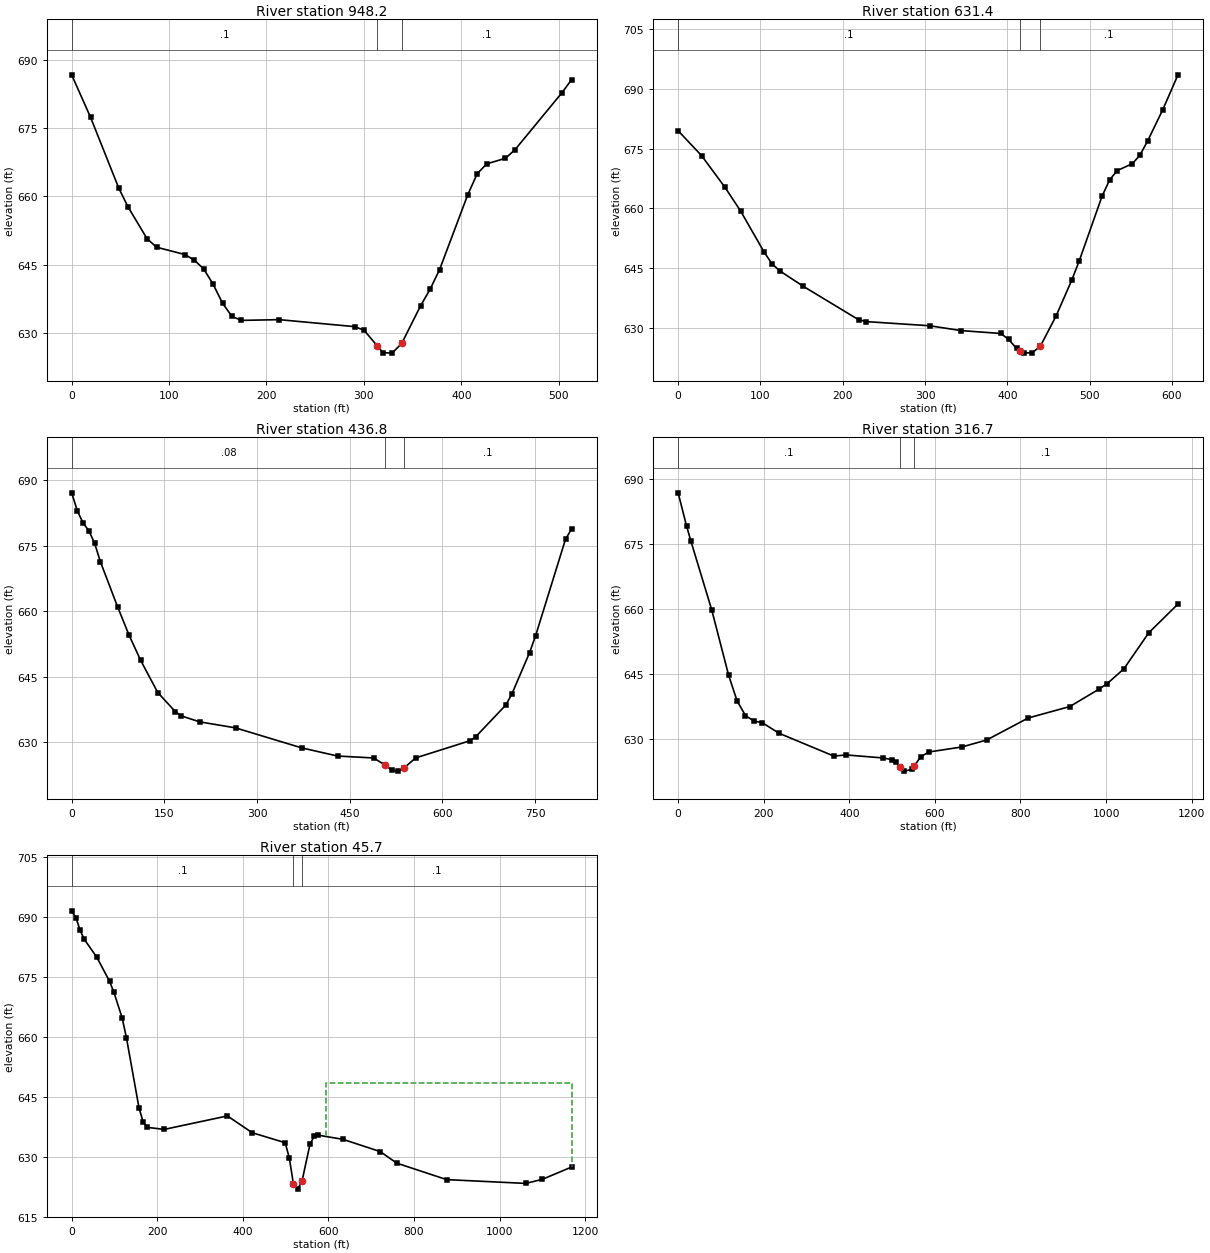
Type RM Length L Ch R = 1 ,948.2   ,314.7,316.8,318.7
XS GIS Cut Line= 2
     1782982.034      542296.834      1782925.61      541786.851
#Sta/Elev= 30
       0   686.7    19.4  677.37    48.4   661.8    58.1   657.6    77.4  650.72
    87.1  648.85   116.2  647.24   125.8  646.02   135.5  644.09   145.2  640.72
   154.9  636.54   164.6  633.64   174.3  632.78     213  632.94   290.4  631.41
   300.1  630.62   313.9  627.13   319.5   625.7   328.9  625.59   338.8  627.72
   358.2     636   367.9   639.6   377.6   643.9   406.6  660.37   416.3  664.98
     426  667.14   445.3  668.38     455  670.23   503.4   682.8   513.1  685.62
#Mann= 3 , 0 , 0
       0      .1       0   313.9    .045       0   338.8      .1       0
Bank Sta=313.9,338.8
XS Rating Curve= 0 ,0
Exp/Cntr=0.3,0.1

Type RM Length L Ch R = 1 ,631.4   ,194.3,194.5,194
XS GIS Cut Line= 4
     1783199.048      542357.598     1783255.471      542216.539
     1783248.961      541899.699     1783227.259       541762.98
#Sta/Elev= 30
       0   679.5    28.5  673.25      57  665.26      76  659.29   104.4  649.03
   113.9  646.09   123.4  644.29   151.9  640.42   219.2     632   228.8  631.52
   305.6  630.48     344  629.26     392  628.54   401.6  627.04   411.2  624.78
   415.5  624.25   420.8   623.6   430.4  623.75     440   625.3   459.2  632.94
   478.1  641.88   487.3  646.77     515  663.02   524.2  667.13   533.4  669.49
   551.9  671.22   561.1  673.37   570.4  676.93   588.8  684.79   607.3  693.56
#Mann= 3 , 0 , 0
       0      .1       0   415.5    .045       0     440      .1       0
Bank Sta=415.5,440
XS Rating Curve= 0 ,0
Exp/Cntr=0.3,0.1

Type RM Length L Ch R = 1 ,436.8   ,125.4,120.2,116.3
XS GIS Cut Line= 4
     1783381.339      542472.615     1783452.954      542342.407
     1783435.593      541789.021     1783346.617      541730.428
#Sta/Elev= 30
       0  687.17     9.3  682.99    18.6  680.23    27.9  678.46    37.2  675.58
    46.4   671.4    74.3  661.03    92.9  654.51   111.4  648.81   139.3  641.36
     168  636.94   177.7  635.99   206.9  634.64   265.2  633.25     372  628.67
   430.3  626.79   488.6  626.35   507.6  624.68   517.7  623.56   527.4  623.33
   537.1  623.97   556.6  626.36     644  630.28   653.7   631.2   702.3  638.46
     712  640.93     741  650.54   750.7   654.4   799.1  676.53   808.8  678.86
#Mann= 3 , 0 , 0
       0     .08       0   507.6    .045       0   537.1      .1       0
Bank Sta=507.6,537.1
XS Rating Curve= 0 ,0
Exp/Cntr=0.3,0.1

Type RM Length L Ch R = 1 ,316.7   ,268.5,271,271.9
XS GIS Cut Line= 4
     1783722.051      542485.636     1783583.162      542149.265
     1783535.419      541795.532     1783526.739      541348.483
#Sta/Elev= 30
       0  686.76    19.7  679.12    29.5  675.75    78.7  659.71     118  644.71
   137.7  638.81   157.4  635.41     177  634.16   196.7  633.77     236  631.33
   363.9  626.08   392.9  626.34   479.7  625.64     499  625.26   508.6  624.73
   518.3  623.55   527.9  622.61   547.2  623.01   551.8  623.78   566.5  625.89
   585.8  627.02     663  628.18   720.9  629.78   818.1  634.86   915.3   637.5
   983.3   641.5  1002.8   642.8  1041.6  646.19    1100  654.53    1168  661.12
#Mann= 3 , 0 , 0
       0      .1       0   518.3    .045       0   551.8      .1       0
Bank Sta=518.3,551.8
XS Rating Curve= 0 ,0
Exp/Cntr=0.3,0.1

Type RM Length L Ch R = 1 ,45.7    ,49,45.7,42.4
XS GIS Cut Line= 4
     1783982.468      542429.212     1783843.579      542092.841
     1783795.836      541739.108     1783787.155       541292.06
#Sta/Elev= 30
       0  691.61     9.8  689.93    19.7  686.75    29.5  684.47      59  679.96
    88.5  673.97    98.4  671.32     118   664.8   127.9   659.9   157.4  642.28
   167.2  638.73     177  637.41   216.4  636.91   363.9  640.28   421.8  636.08
     499  633.57   508.6  629.73   518.3   623.2   527.9  621.96   538.2  623.92
   556.9  633.21   566.5  635.15   576.2  635.46     634  634.42   720.9  631.36
   759.7  628.46   876.4  624.34  1061.1  623.39    1100  624.42    1168  627.48
#Mann= 3 , 0 , 0
       0      .1       0   518.3    .045       0   538.2      .1       0
#XS Ineff= 2 , 0
                          594.15          648.57
Permanent Ineff=
       F       F
Bank Sta=518.3,538.2
XS Rating Curve= 0 ,0
Exp/Cntr=0.3,0.1

Chan Stop Cuts=-1
Use User Specified Reach Order=0
Composite Channel Slope=5